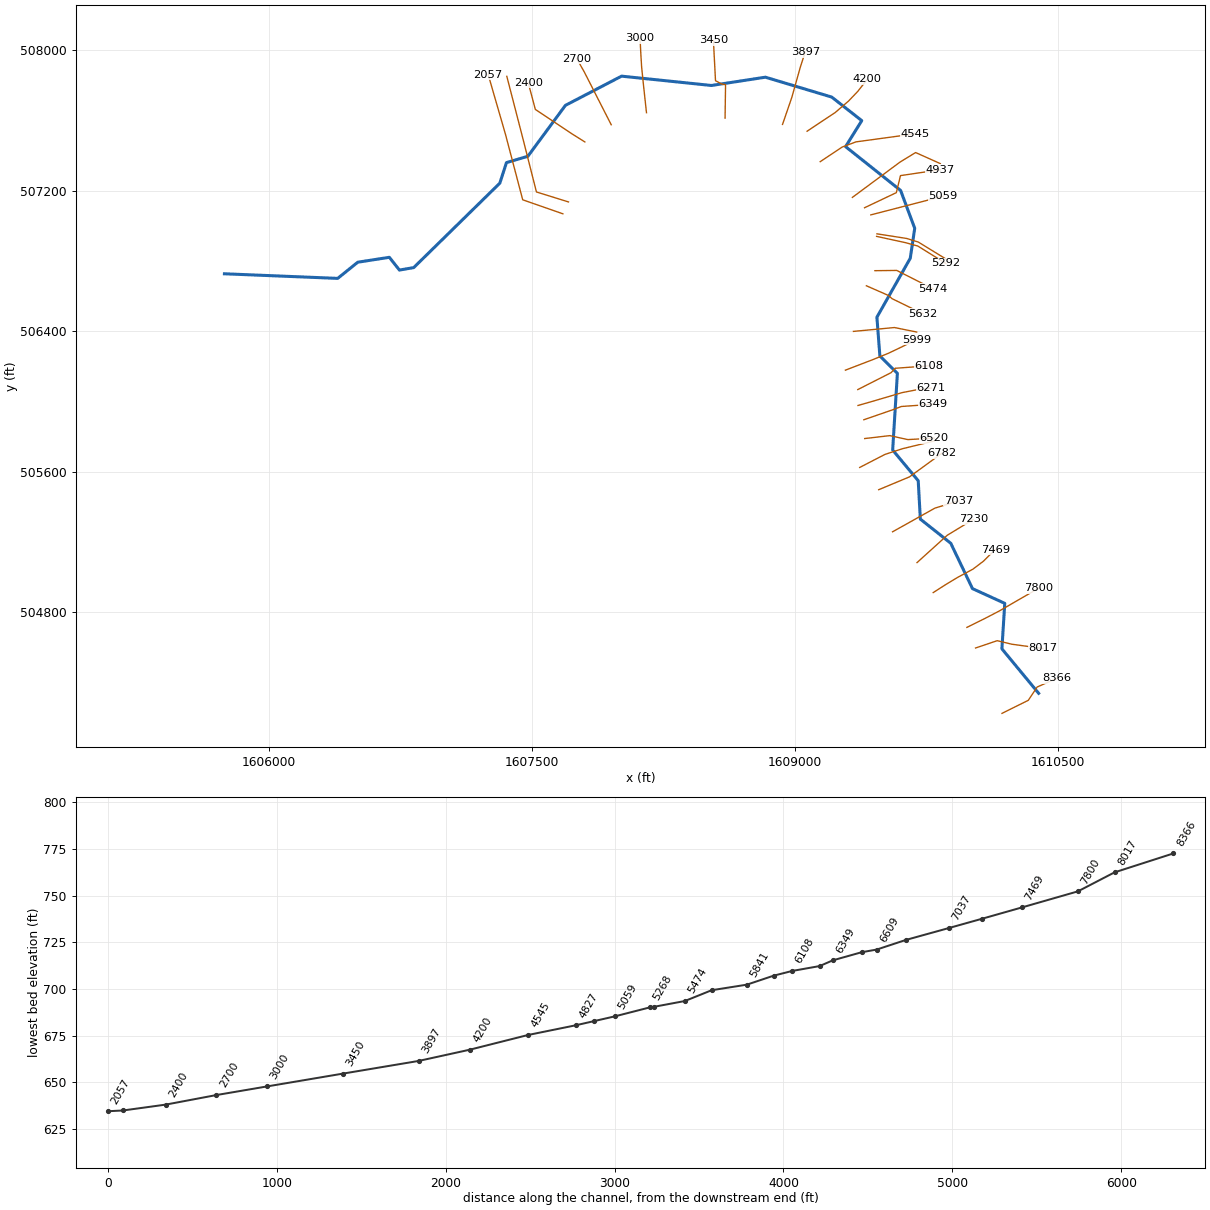
--- FishRn.prj (project) ---

Proj Title=FishRn
Current Plan=p01
Default Exp/Contr=0,0
English Units
Geom File=g01
Flow File=f01
Plan File=p01
BEGIN DESCRIPTION:
---------- MODELED AS PART OF WVEM CTP PROGRAM, 2025----------
Stream Name: Fish Run
Flood Zone: AFH
Marshall County, WV
HEC-RAS Version: RAS 6.6
Vertical Datum: NAVD88
Projection: NAD 1983 StatePlane West Virginia N FIPS 4701 (US Feet)
Terrain: 1-meter West Virginia FEMA R3 South Central (collected 2018-2019)
Land Use: 2024 NLCD
Hydrologic Method:
Duda et al., "Estimation of magnitude and frequency of floods for rural, unregulated streams in and near Virginia and West Virginia." September 8, 2025.
Additional Model Notes:
None
END DESCRIPTION:
DSS Export Rating Curves= 0
DSS Export Rating Curve Sorted= 0
DSS Export Volume Flow Curves= 0
DXF OffsetX= 0
DXF OffsetY= 0
DXF ScaleX= 0
DXF ScaleY= 0

--- FishRn.p01 (plan) ---

Plan Title=Floodplain
Program Version=6.60
Short Identifier=Floodplain
Geom File=g01
Flow File=f01
Subcritical Flow
K Sum by GR= 0
Std Step Tol= 0.01
Critical Tol= 0.01
Num of Std Step Trials= 20
Max Error Tol= 0.3
Flow Tol Ratio= 0.001
Split Flow NTrial= 30
Split Flow Tol= 0.02
Split Flow Ratio= 0.02
Log Output Level= 0
Friction Slope Method= 1
Unsteady Friction Slope Method= 2
Unsteady Bridges Friction Slope Method= 1
Parabolic Critical Depth
Global Vel Dist= 0 , 0 , 0
Global Log Level= 0
CheckData=False
Encroach Param=-1 ,0,0, 0
Flow Ratio Tolerance=0.1
Flow Ratio Min Ratio=0.5
Flow Ratio Max Ratio=4
Flow Ratio Max Iterations= 10
Mapping Interval=1HOUR
Computation Time Step Use Courant=        0
Computation Time Step Use Time Series=    0
Computation Time Step Count To Double=0
Computation Time Step Max Doubling=0
Computation Time Step Max Halving=0
Computation Time Step Residence Courant=0
Run HTab= 0
Run UNet= 0
Run Sediment= 0
Run PostProcess= 0
Run WQNet= 0
Run RASMapper=-1
UNET Theta= 0
UNET Theta Warmup= 0
UNET ZTol= 0
UNET ZSATol= 0
UNET MxIter= 0
UNET Max Iter WO Improvement= 0
UNET MaxInSteps= 0
UNET DtIC= 0
UNET DtMin= 0
UNET MaxCRTS= 0
UNET WFStab= 0
UNET SFStab= 0
UNET WFX= 1
UNET SFX= 1
UNET Gravity=32.17405
UNET 1D Methodology=Finite Difference
UNET DSS MLevel= 1
UNET Pardiso=0
UNET DZMax Abort= 0
UNET Use Existing IB Tables= 0
UNET Froude Reduction=False
UNET Froude Limit= 0
UNET Froude Power= 0
UNET D1 Cores= 0
UNET WindReference=Eulerian
UNET WindDragFormulation=Hsu (1988)
UNET D2 Coriolis=0
UNET D2 Cores= 0
UNET D2 Theta= 1
UNET D2 Theta Warmup= 1
UNET D2 Z Tol= 0.01
UNET D2 Volume Tol= 0.01
UNET D2 Max Iterations= 20
UNET D2 Advanced Convergence=0
UNET D2 WS Max Tol=0.15
UNET D2 WS RMS Tol=0.002
UNET D2 WS Stall Tol=1
UNET D2 Equation= 0
UNET D2 RampUpFraction=0.1
UNET D2 TimeSlices= 1
UNET D2 Turbulence Formulation=Non-Conservative (original)
UNET D2 Eddy Viscosity=0.3
UNET D2 Transverse Eddy Viscosity=0.1
UNET D2 Smagorinsky Mixing=0
UNET D2 BCVolumeCheck=0
UNET D2 Cores=0
UNET D2 SolverType=PARDISO (Direct)
UNET D2 Minimum Iterations= 3
UNET D2 Maximum Iterations= 30
UNET D2 Restart Number= 10
UNET D2 Relaxation Coeff=1.3
UNET D2 SOR Precondition Iterations= 10
UNET D2 ILUT Maximum Fill= 8
UNET D2 ILUT Tolerance=1E-08
UNET D2 Convergence Tolerance=0.00001
PS Theta= 1
PS WS Tol= 0.01
PS Volume Tol= 0.01
PS Max Iterations= 20
PS Equation= 0
PS Advance Time Step=-1
PS Target Courant=0.9
PS Time Slices= 1
PS Iterate With 2D=0
PS Project Initial WSE from DS=-1
PS Ramp Up Initial WSE from US=-1
PS Cores=0
UNET D1D2 MaxIter= 0
UNET D1D2 ZTol=0.01
UNET D1D2 QTol=0.1
UNET D1D2 MinQTol=1
Write IC File= 0
Write IC File at Fixed DateTime=0
Write IC File at Sim End=0
Echo Input=False
Echo Parameters=False
Echo Output=False
Write Detailed= 0
HDF Write Warmup=0
HDF Write Time Slices=0
HDF Flush=0
HDF Compression= 1
HDF Chunk Size= 1
HDF Spatial Parts= 1
HDF Use Max Rows=0
HDF Fixed Rows= 1
Calibration Method= 0
Calibration Iterations= 20
Calibration Max Change=0.05
Calibration Tolerance=0.2
Calibration Maximum=1.5
Calibration Minimum=0.5
Calibration Optimization Method= 1
WQ AD Non Conservative
WQ ULTIMATE=-1
WQ Max Comp Step=1HOUR
WQ Output Interval=15MIN
WQ Output Selected Increments= 0
WQ Create Restart=0
WQ Fixed Restart=0
WQ System Summary=0
WQ Write To DSS=0
Sorting and Armoring Iterations= 10
XS Update Threshold= 0.02
Bed Roughness Predictor= 0
Processes Affected by Predictor=Sediment Only
Hydraulics Update Threshold= 0.02
Energy Slope Method= 1
Volume Change Method= 1
Sediment Retention Method= 0
Sediment TS Multiplier= 1
Warm Up Method= 0
XS Weighting Method= 0
Number of US Weighted Cross Sections= 1
Number of DS Weighted Cross Sections= 1
Upstream XS Weight=0
Main XS Weight=1
Downstream XS Weight=0
Number of DS XS's Weighted with US Boundary= 1
Upstream Boundary Weight= 1
Weight of XSs Associated with US Boundary= 0
Number of US XS's Weighted with DS Boundary= 1
Downstream Boundary Weight= 0.5
Weight of XSs Associated with DS Boundary= 0.5
Percentile Method= 0
Sediment Output Level= 3
Mass or Volume Output= 0
Output Increment Type= 1
Profile and TS Output Increment= 1
Transport Output Increment 1
XS Output Flag= 0
XS Output Increment= 10
Read HDF5 Sediment Hotstart= 0
Sediment Hotstart Type= 0
Write Gradation File= 0
Read Gradation Hotstart= 0
Write HDF5 File= 1
Write Binary Output= 1
Write DSS Sediment File= 0
DSS Sediment Output Type= 1
SV Curve= 0
Specific Gage Flag= 0
Subcell Erosion Methods= 0
Subcell Deposition Methods= 0
Advection Scheme= 1
Matrix Solver= 0
Implicit Weighting Factor= 1
Maximum Outer Loop Convergence Iterations= 5
Convergence Maximum Absolute= 0.001
Convergence RMSE= 0.0001
Grain Fractions Max Abs Error= 0.001
Max Subgrid Regions= 1
Max Subgrid Length Scale= 3.402823E+38
Initial Layer Thickness= 3
Min Layer Thickness= 0.1
Max Layer Thickness= 6
Number of Layers= 5

--- FishRn.f01 (steady flow) ---

Flow Title=Flow
Program Version=6.60
Number of Profiles= 1
Profile Names=P100yr
River Rch & RM=FishRn,Main,8366
    1060
River Rch & RM=FishRn,Main,4200
    1100
River Rch & RM=FishRn,Main,2057
    1250
Boundary for River Rch & Prof#=FishRn,Main            , 1
Up Type= 0
Dn Type= 3
Dn Slope=0.02301
DSS Import GetInterval= 0
DSS Import GetPeak= 0
DSS Import FillOption= 0

--- FishRn.g01 (geometry) ---

Geom Title=Geometry
Program Version=6.60

River Reach=FishRn          ,Main
Reach XY= 30
1610387.89625645504337.976739785     1610178.625      504591.047
     1610194.888      504850.165     1610010.903      504934.055
     1609887.165      505192.428     1609713.798      505329.873
     1609701.693      505548.534     1609556.049      505723.463
     1609582.991      506160.005     1609483.157      506259.122
     1609466.242      506479.798     1609656.399        506815.6
     1609681.779      506986.233     1609601.343      507201.771
     1609287.798       507451.28     1609379.898      507599.379
     1609208.927      507733.565     1608830.681      507846.799
     1608523.445      507799.618     1608011.013      507852.717
     1607691.142      507686.384     1607477.161      507396.377
      1607355.15      507360.346     1607317.341      507243.264
     1606826.526      506762.306     1606745.004      506748.331
     1606687.659      506820.937     1606507.725      506793.079
      1606393.43      506700.918     1605747.871       506727.15

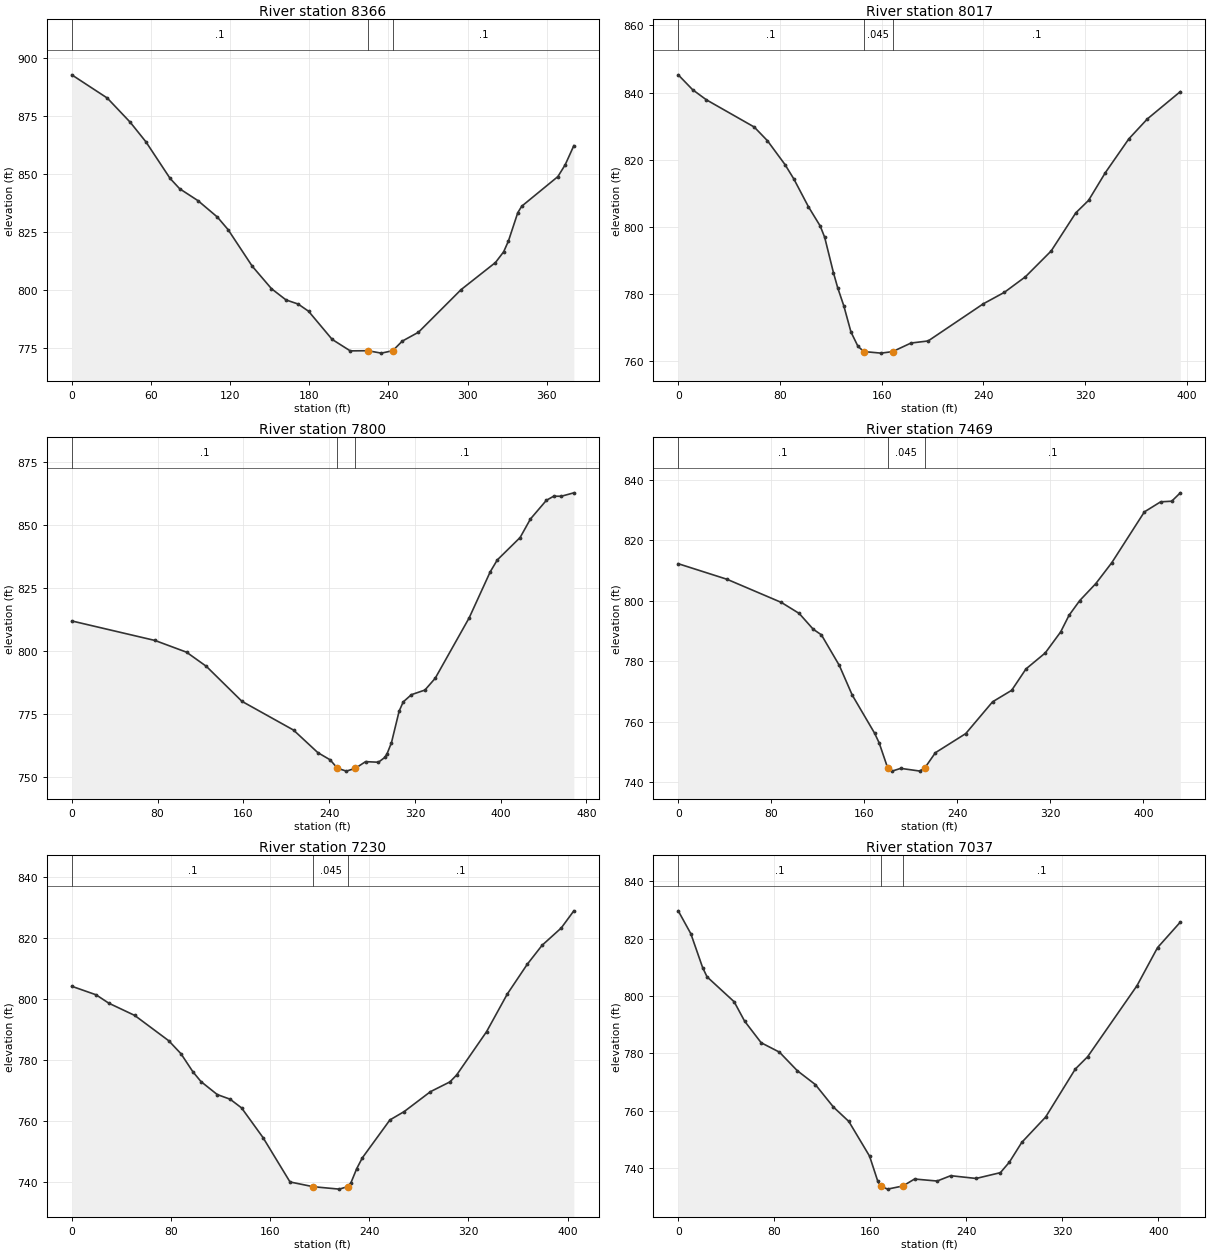
Type RM Length L Ch R = 1 ,8366    ,361.2,348.6,335.1
XS GIS Cut Line= 4
1610179.05135168504223.5361524471610329.13337139504298.073531366
1610379.49646526504373.6181721621610491.30253364504422.974004149
#Sta/Elev= 30
       0  892.56    26.9  882.56    44.3  872.13    56.2   863.7    74.5  847.95
    81.8  843.47    95.7  838.33   110.4  831.26   118.5  825.85   136.8   810.1
   151.4   800.4   162.4  795.57   171.6  793.79   179.5  790.69   197.4  778.55
   211.1  773.61   224.3  773.68   234.7  772.64  243.31773.6876   250.5   777.8
   262.8  781.64   295.1  799.99   321.2  811.69   327.4  816.31     331  820.93
   338.1  833.16   341.1  835.95   368.5  848.71     374  853.76   380.6  862.05
#Mann= 3 ,-1,0
       0      .1       0   224.3    .045       0  243.31      .1       0
Bank Sta=224.3,243.31
XS Rating Curve= 0 ,0
Exp/Cntr(USF)=0,0
Exp/Cntr=0.3,0.1

Type RM Length L Ch R = 1 ,8017    ,210.2,217.2,223.3
XS GIS Cut Line= 4
1610028.36388137504595.8401581341610151.85528099504637.520784011
1610235.45801681504617.3755464651610412.49876725504593.169836545
#Sta/Elev= 30
       0  845.28    11.3  840.86    22.1  837.86    59.8  829.75    70.2  825.67
      84  818.58      91  814.27   102.4  806.06   111.7   800.3   115.2  796.96
   122.1  786.44   125.4  782.01   130.3  776.51   135.9  768.77   141.4  764.51
     146  762.96   159.5  762.49   168.6  762.93   183.1  765.49   196.6  766.11
     240  777.16   256.6  780.58   273.1  785.19   293.4  792.88   312.8  804.23
   322.8  807.92     336  816.16   354.5  826.23   369.1  832.17     395  840.28
#Mann= 3 ,-1,0
       0      .1       0     146    .045       0   168.6      .1       0
Bank Sta=146,168.6
XS Rating Curve= 0 ,0
Exp/Cntr(USF)=0,0
Exp/Cntr=0.3,0.1

Type RM Length L Ch R = 1 ,7800    ,337.1,330.7,328.7
XS GIS Cut Line= 6
1609979.24972583504713.3281413321610080.24985193 504763.32246393
1610162.78347951504806.0858298391610249.32628542504856.189076096
1610314.23330784504893.7667568331610389.95789392504937.607548416
#Sta/Elev= 30
       0  811.93    77.6  804.18     107  799.53   125.5  793.91   158.7  780.01
   206.8   768.6   229.5  759.63   240.9   756.8  247.74753.4471   256.1   752.3
  264.56753.4469     274  756.07     286  755.83     292  757.78     294  759.18
   298.1  763.56   305.3  776.15   309.1  779.79   316.7  782.65   329.3  784.49
   338.9  789.16   370.6  813.17   390.2  831.42   396.8  836.15   418.1  845.06
   427.7   852.4   442.6  859.83   449.4  861.46   456.5  861.44   468.2   862.8
#Mann= 3 ,-1,0
       0      .1       0  247.74    .045       0  264.56      .1       0
Bank Sta=247.74,264.56
XS Rating Curve= 0 ,0
Exp/Cntr(USF)=0,0
Exp/Cntr=0.3,0.1

Type RM Length L Ch R = 1 ,7469    ,233.8,239.4,240.6
XS GIS Cut Line= 6
1609787.20039431504911.5397677891609861.14315981504958.778190362
1609925.44814931504997.5487821121610013.49521731505044.958792286
1610073.92423031505090.6256957081610139.82928223505156.371955278
#Sta/Elev= 30
       0  812.24      42  807.09    88.7  799.44     104  795.81   116.1  790.58
   123.1  788.74   138.5  778.64   149.6  768.84   168.8  756.27   172.7   753.1
   180.1  744.75   183.8  743.71   191.3  744.62   207.6  743.74  211.94744.7345
   221.1  749.79   247.2  756.11   270.3  766.62   286.7  770.41     299  777.48
   315.5  782.73   328.8  789.69     336  795.18   345.2  800.05   359.1   805.7
   372.8  812.59   400.8  829.36   414.8  832.69   424.3  832.89   431.7  835.66
#Mann= 3 ,-1,0
       0      .1       0   180.1    .045       0  211.94      .1       0
Bank Sta=180.1,211.94
XS Rating Curve= 0 ,0
Exp/Cntr(USF)=0,0
Exp/Cntr=0.3,0.1

Type RM Length L Ch R = 1 ,7230    ,191.6,192.4,188.7
XS GIS Cut Line= 3
1609694.96818426505082.2887113061609867.18037164505237.996647002
1610015.01329384505327.731637383
#Sta/Elev= 30
       0  804.19    19.6  801.39    29.9  798.63    50.8  794.61    78.3  786.28
    88.1  782.04    97.8  776.06   104.3  772.87   117.4  768.62   127.8  767.09
     137  764.24   154.3   754.5   176.1  739.91   194.9  738.35   215.8  737.56
  222.55738.3727   225.1   739.5   229.9  744.28   234.4  747.81   256.7  760.29
   268.2  763.03   289.4  769.57   305.1  772.78   310.5  775.03   334.7  789.29
   351.4  801.64   367.5  811.41   379.5  817.66   394.9  823.32   405.1  828.97
#Mann= 3 ,-1,0
       0      .1       0   194.9    .045       0  222.55      .1       0
Bank Sta=194.9,222.55
XS Rating Curve= 0 ,0
Exp/Cntr(USF)=0,0
Exp/Cntr=0.3,0.1

Type RM Length L Ch R = 1 ,7037    ,254,255.9,255.8
XS GIS Cut Line= 3
1609555.51666509505257.6243231771609796.99655986505392.638944141
1609932.60595889505433.678630689
#Sta/Elev= 30
       0  829.66    10.5  821.68    20.3  809.91      24  806.66    46.6  797.97
    55.3  791.22    69.1  783.69    84.3  780.42    99.2  773.95   114.2  769.13
   129.3  761.28   142.1  756.28   159.4  744.18   166.2   735.5   168.6  733.76
   174.4  732.68  187.21733.7845   196.9   736.2   215.7   735.5     227  737.36
   248.2   736.4   268.4  738.42   275.9  742.09   286.2  748.96   306.1   757.8
   330.8  774.52   341.1  778.83   382.2  803.57   399.3  816.82   418.3  825.73
#Mann= 3 ,-1,0
       0      .1       0   168.6    .045       0  187.21      .1       0
Bank Sta=168.6,187.21
XS Rating Curve= 0 ,0
Exp/Cntr(USF)=0,0
Exp/Cntr=0.3,0.1

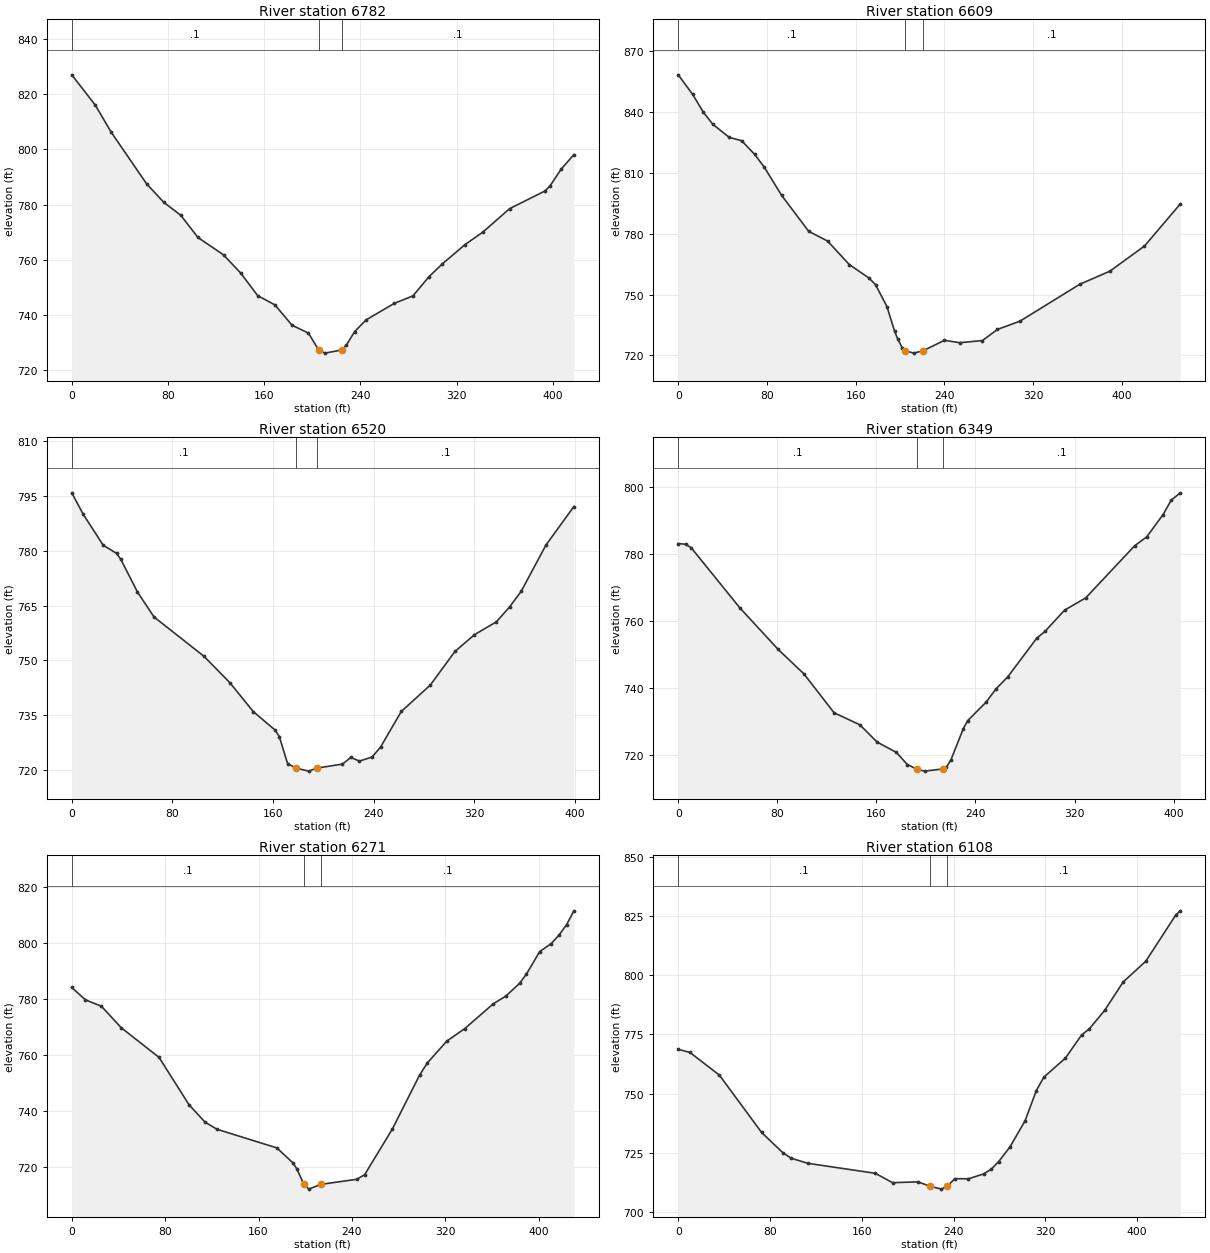
Type RM Length L Ch R = 1 ,6782    ,175.1,172.5,170.4
XS GIS Cut Line= 3
1609476.41118233505497.3198837421609651.87071177 505570.47758585
1609835.65713414505704.302650682
#Sta/Elev= 30
       0  826.99    19.6     816    32.6  806.35    62.2  787.55    76.4  780.89
    90.7  776.11   104.9  768.13   126.2  761.81   140.4  755.25   154.6  747.07
   168.9  743.72   183.1  736.38   196.8   733.5  205.23727.3981   210.5  726.27
   224.6  727.43   228.2  729.12   235.2  734.08   244.6  738.27   268.1  744.28
   283.6  746.98   297.1  753.99   308.2  758.61   326.8  765.51   341.7  770.05
     364  778.56   393.1  784.89   397.3  786.59   406.7  792.77   417.4   798.1
#Mann= 3 ,-1,0
       0      .1       0  205.23    .045       0   224.6      .1       0
Bank Sta=205.23,224.6
XS Rating Curve= 0 ,0
Exp/Cntr(USF)=0,0
Exp/Cntr=0.3,0.1

Type RM Length L Ch R = 1 ,6609    ,93.3,89.1,84.7
XS GIS Cut Line= 6
1609368.21485868505624.1537474991609445.97881076505664.248483583
1609512.63845433505698.6198059171609611.49127501505730.728009418
1609694.93369342 505750.997982011609792.43251418505774.786976427
#Sta/Elev= 30
       0  858.33    12.9  848.76    22.7  839.86    31.3  833.88    46.1  827.45
    57.2  825.86      69  819.05    77.6  812.77    93.3  798.84   117.7  781.14
   134.7  776.37   154.2  764.79   171.9  758.18   177.9  754.86   188.2  744.07
   195.1  731.86   197.9  728.16     202  723.65   204.5722.3453   212.4  721.12
   220.8722.3112     240  727.44   253.8  726.26   274.3  727.32   287.8   732.8
   308.1  736.87   362.1  755.09   389.1  761.49   420.4  773.93   452.7  794.68
#Mann= 3 ,-1,0
       0      .1       0   204.5    .045       0   220.8      .1       0
Bank Sta=204.5,220.8
XS Rating Curve= 0 ,0
Exp/Cntr(USF)=0,0
Exp/Cntr=0.3,0.1

Type RM Length L Ch R = 1 ,6520    ,166.8,171,178
XS GIS Cut Line= 4
1609396.71092149505788.7611360421609540.05243538505805.414921888
1609642.35426272505782.8133553831609792.23833533505791.140248306
#Sta/Elev= 30
       0  795.91     9.2  789.98      25  781.56    35.7   779.3      39  777.67
    52.2  768.77    65.4  761.91     105  751.18   125.7  743.91   144.3  736.01
   161.5  730.97     165  729.17   171.6  721.76   178.3  720.51   188.4  719.69
   194.8  720.51   215.2  721.62   221.9  723.43   228.7  722.44   238.7  723.54
   245.5  726.27     262  736.03     285  743.23   304.7  752.48   320.2  757.06
   337.6  760.58   348.1  764.66   357.3  768.92     377  781.59   399.2  792.16
#Mann= 3 ,-1,0
       0      .1       0   178.3    .045       0   194.8      .1       0
Bank Sta=178.3,194.8
XS Rating Curve= 0 ,0
Exp/Cntr(USF)=0,0
Exp/Cntr=0.3,0.1

Type RM Length L Ch R = 1 ,6349    ,77.9,77.6,76.5
XS GIS Cut Line= 4
1609391.95269697505895.8211879071609555.51666509 505952.32510417
1609605.47802263505971.3580022791609783.91144241505983.848341663
#Sta/Elev= 30
       0  783.13     5.9  782.94    10.4  781.92    49.7     764    80.7  751.59
   101.5  744.31   125.8  732.74   146.7  729.13   160.5  724.02   176.1  720.93
     185   717.3   193.1715.8723     199  715.34  213.91716.0059   216.6  716.59
   220.1  718.62   230.1  727.92   233.6  730.34   248.6  735.89   256.7  739.89
     266   743.4   289.5  754.95   296.1  756.95   311.9  763.28     329  766.95
   368.5  782.46   378.3  785.15   391.5  791.78   398.1  796.08   405.4  798.25
#Mann= 3 ,-1,0
       0      .1       0   193.1    .045       0  213.91      .1       0
Bank Sta=193.1,213.91
XS Rating Curve= 0 ,0
Exp/Cntr(USF)=0,0
Exp/Cntr=0.3,0.1

Type RM Length L Ch R = 1 ,6271    ,155.6,163,163.8
XS GIS Cut Line= 6
1609358.51802768505977.128224802 1609442.6691061 506001.11570963
1609514.62106192506022.2797093061609610.55722176 506050.49750064
1609685.57708484506065.0785082251609776.14416093506076.175270808
#Sta/Elev= 30
       0  784.13    11.7  779.71    25.4  777.43    42.4  769.77    74.8   759.2
   100.5  742.33   114.1  736.18   124.4  733.61   175.7  726.97   189.4  721.68
   192.8  719.54  198.75714.1125   203.1  712.28   213.3  713.97   244.1  715.78
   250.9  717.39   274.6  733.62     298  752.87   304.7  757.26   321.4  765.03
   336.7  769.46   361.2  778.31   371.9  781.04   383.7  785.59   389.6  788.89
   400.9  796.89   410.8  799.74   417.4  802.75     424  806.49   430.2  811.42
#Mann= 3 ,-1,0
       0      .1       0  198.75    .045       0   213.3      .1       0
Bank Sta=198.75,213.3
XS Rating Curve= 0 ,0
Exp/Cntr(USF)=0,0
Exp/Cntr=0.3,0.1

Type RM Length L Ch R = 1 ,6108    ,114.3,109.4,104.9
XS GIS Cut Line= 4
1609357.45556914506067.7120489581609547.18977217506164.066095637
1609570.38611674506189.0467744051609760.71509784506202.726669921
#Sta/Elev= 30
       0  768.68    10.2  767.37    35.9  757.77    72.7  733.57    91.1  725.07
    98.5  722.68   113.2  720.53   171.8  716.34   186.8  712.37   208.9  712.73
  219.38710.9036   229.5  709.65  234.61710.8972   241.1  714.06     253  714.01
   266.2  716.07   272.8  718.02   279.3  721.24   289.2  727.47   302.4  738.56
   312.2  751.28   318.8  756.97   337.5  764.95   351.7  774.79   358.3  777.28
   371.7  785.09   387.9  797.13   407.6  805.87   433.9  825.52   437.7  827.16
#Mann= 3 ,-1,0
       0      .1       0  219.38    .045       0  234.61      .1       0
Bank Sta=219.38,234.61
XS Rating Curve= 0 ,0
Exp/Cntr(USF)=0,0
Exp/Cntr=0.3,0.1

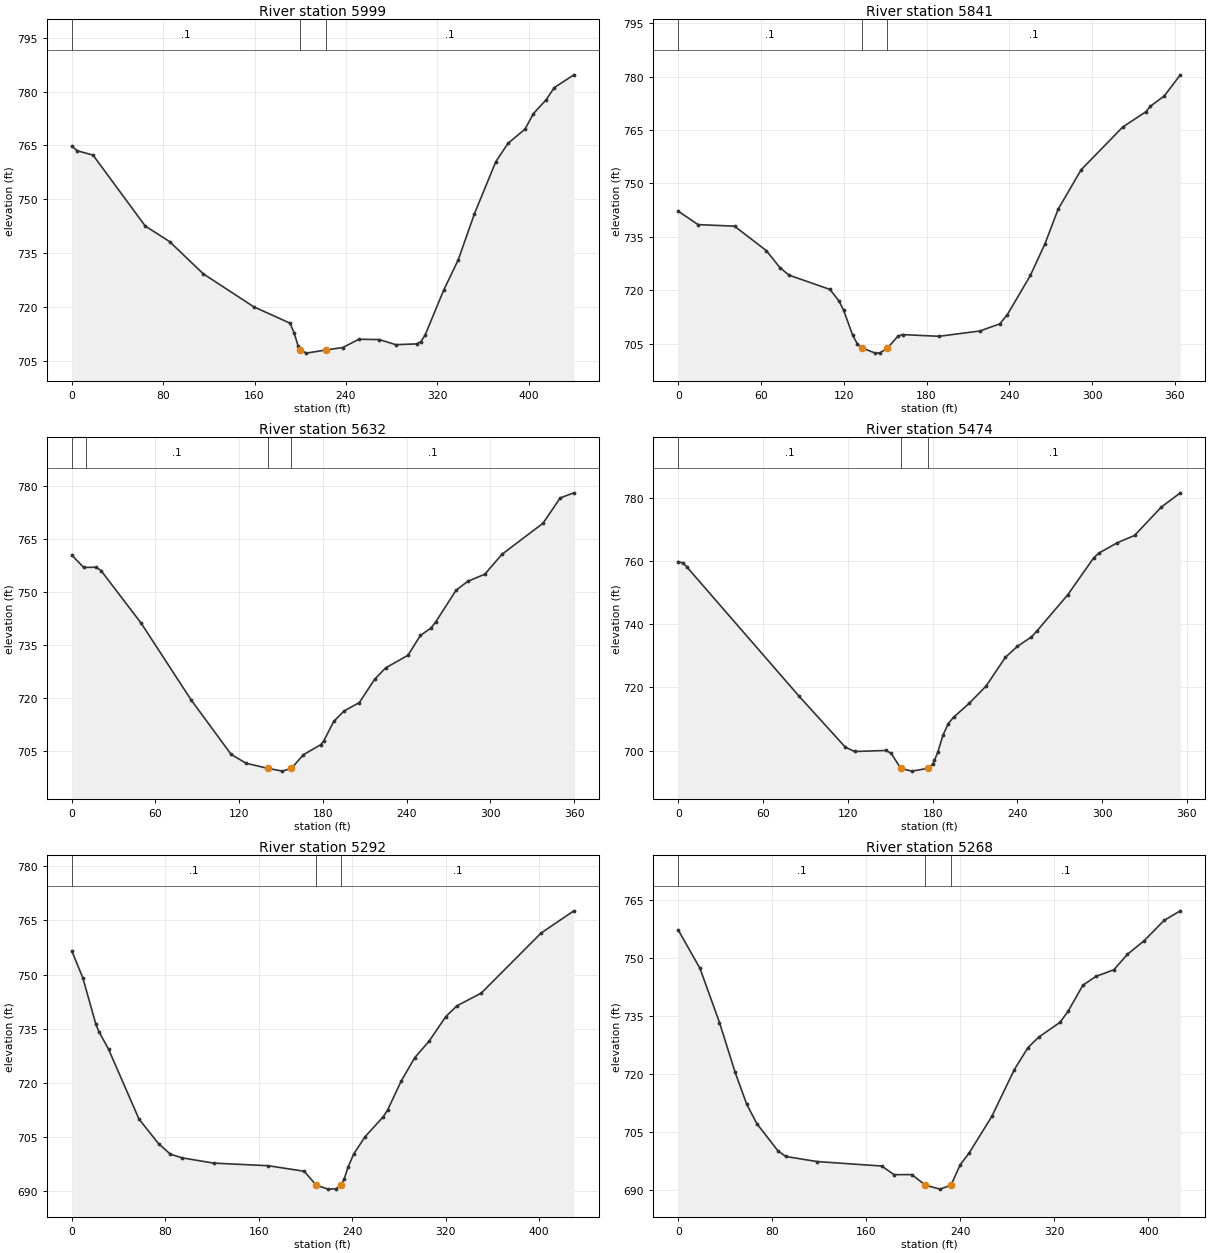
Type RM Length L Ch R = 1 ,5999    ,161.8,158.2,155
XS GIS Cut Line= 6
1609286.59461509506178.2103821781609368.29753567506209.529873341
1609438.32823551506236.3749639991609531.39530659506274.220032677
1609603.78361325506308.6983101671609690.21618317506351.486938506
#Sta/Elev= 30
       0  764.82     4.8  763.52    18.6  762.32    64.3  742.56    85.6  738.22
   115.1  729.24   159.4  720.03   191.1  715.48   194.8  712.66   198.3  709.02
  200.25708.0361   205.4  707.13   222.9708.0352   237.3  708.69   251.4     711
   269.3   710.9   283.7  709.49     302   709.7   305.7  710.34   309.3  712.11
   325.6  724.66   338.4  733.14   352.6  746.01   371.3   760.5     382   765.6
   396.9  769.57   404.2  773.87   415.2  777.68   422.5  781.12   439.6  784.68
#Mann= 3 ,-1,0
       0      .1       0  200.25    .045       0   222.9      .1       0
Bank Sta=200.25,222.9
XS Rating Curve= 0 ,0
Exp/Cntr(USF)=0,0
Exp/Cntr=0.3,0.1

Type RM Length L Ch R = 1 ,5841    ,215.8,208.8,200.9
XS GIS Cut Line= 3
1609332.47489038506399.0034316741609566.22267028506421.010220113
1609692.91039832506395.434763279
#Sta/Elev= 30
       0   742.2    14.4  738.44    40.8     738    63.9  731.12    73.7  726.36
    80.3  724.24     110  720.22   116.6  716.97   119.9  714.36   126.5  707.35
   129.9  704.88   133.1  703.79   142.9  702.32   146.2  702.39  151.67703.7454
   159.4  707.13   162.7  707.53   189.1  707.05   218.7  708.54   233.1  710.55
   238.6  713.13   255.3  724.16   265.9  733.07   275.4  742.75   292.1  753.85
   322.2  765.84     339  770.15   342.3  771.71   352.4  774.61     364  780.53
#Mann= 3 ,-1,0
       0      .1       0   133.1    .045       0  151.67      .1       0
Bank Sta=133.1,151.67
XS Rating Curve= 0 ,0
Exp/Cntr(USF)=0,0
Exp/Cntr=0.3,0.1

Type RM Length L Ch R = 1 ,5632    ,155,158.5,159.1
XS GIS Cut Line= 4
1609406.30994909 506658.905150321609533.06704357506603.258524991
1609552.34850003506585.5575157841609727.74255677506499.946633553
#Sta/Elev= 30
       0  760.42     8.5  756.92    17.5  756.97      21  756.02    49.7  741.17
    85.5  719.49   114.2  704.06     125  701.55   140.4  700.12     151  699.33
  157.41700.1311     166  703.97   178.3  706.78   180.5  707.82   187.8  713.43
   195.1  716.32   206.1  718.73     217  725.27   224.9  728.51   240.9  732.08
   249.9  737.72   257.2  739.71   260.8   741.5   275.4  750.47   283.7  752.97
     296  755.01   308.3  760.63   337.7  769.41     350  776.56   359.8  778.01
#Mann= 4 ,-1,0
       0     .08       0      10      .1       0   140.4    .045       0
  157.41      .1       0
Bank Sta=140.4,157.41
XS Rating Curve= 0 ,0
Exp/Cntr(USF)=0,0
Exp/Cntr=0.3,0.1

Type RM Length L Ch R = 1 ,5474    ,178.6,181.9,182.4
XS GIS Cut Line= 3
1609454.94036234 506744.831082961609579.18111498506746.257075345
1609785.37262117506642.029935765
#Sta/Elev= 30
       0  759.78     3.4  759.36       6  758.16    85.5  717.25   118.3   701.1
   124.9  699.76     147  700.08   150.7  699.19  157.49694.4106   165.4  693.55
   176.5  694.41   180.1  695.77   181.3  696.93   183.7  699.57   187.4     705
   191.1   708.6   194.8  710.57   205.8  714.95   217.9  720.47   231.5  729.53
   239.9  732.96   249.9  735.97   253.6  737.75   275.6  749.28     294  760.99
   297.7   762.5   310.7  765.77   322.9  768.07   341.8  777.02   355.3  781.55
#Mann= 3 ,-1,0
       0      .1       0  157.49    .045       0   176.5      .1       0
Bank Sta=157.49,176.5
XS Rating Curve= 0 ,0
Exp/Cntr(USF)=0,0
Exp/Cntr=0.3,0.1

Type RM Length L Ch R = 1 ,5292    ,23.7,23.6,23
XS GIS Cut Line= 4
1609464.48618314506940.1532626331609630.43660647506904.172861114
1609699.46023387506885.0812194921609859.53630594506785.951541839
#Sta/Elev= 30
       0  756.58     9.5  749.04    20.6  736.25    23.2  734.18    31.5  729.27
    57.5  709.93    74.3  703.07    84.4  700.17    94.5  699.14   121.3  697.69
   168.3  696.96   198.9  695.43   209.2  691.57   219.4  690.47   226.2  690.56
  230.32  691.57     233  693.15   236.4  696.55   241.4  700.27   251.1  705.04
   266.6  710.55   270.4  712.49     282   720.5   293.6  726.97   305.8   731.5
   320.1  738.33   329.6  741.31   350.5  744.86   401.6  761.49   429.7  767.67
#Mann= 3 ,-1,0
       0      .1       0   209.2    .045       0  230.32      .1       0
Bank Sta=209.2,230.32
XS Rating Curve= 0 ,0
Exp/Cntr(USF)=0,0
Exp/Cntr=0.3,0.1

Type RM Length L Ch R = 1 ,5268    ,203.8,209,215.2
XS GIS Cut Line= 4
1609466.35416658506954.7226041191609636.19634762506928.288023412
1609702.28279939506907.8012233631609860.89028364506810.654139263
#Sta/Elev= 30
       0  757.19    18.5  747.26    35.1  733.26    48.4  720.38    58.3  712.11
    66.9   707.1    84.9  700.06    91.5  698.62   118.1  697.31   173.1  696.15
   183.6  693.92   198.7  693.94  210.23691.2057   222.7  690.18  232.03691.1987
   239.9  696.51   247.5  699.53   266.7  708.96   285.9  721.08   297.5  726.77
   306.5  729.45   324.8  733.32   331.7   736.2   344.2   742.9   355.2  745.17
   370.6  746.91   382.1  750.89   396.4  754.43   413.3  759.66   427.1  762.14
#Mann= 3 ,-1,0
       0      .1       0  210.23    .045       0  232.03      .1       0
Bank Sta=210.23,232.03
XS Rating Curve= 0 ,0
Exp/Cntr(USF)=0,0
Exp/Cntr=0.3,0.1

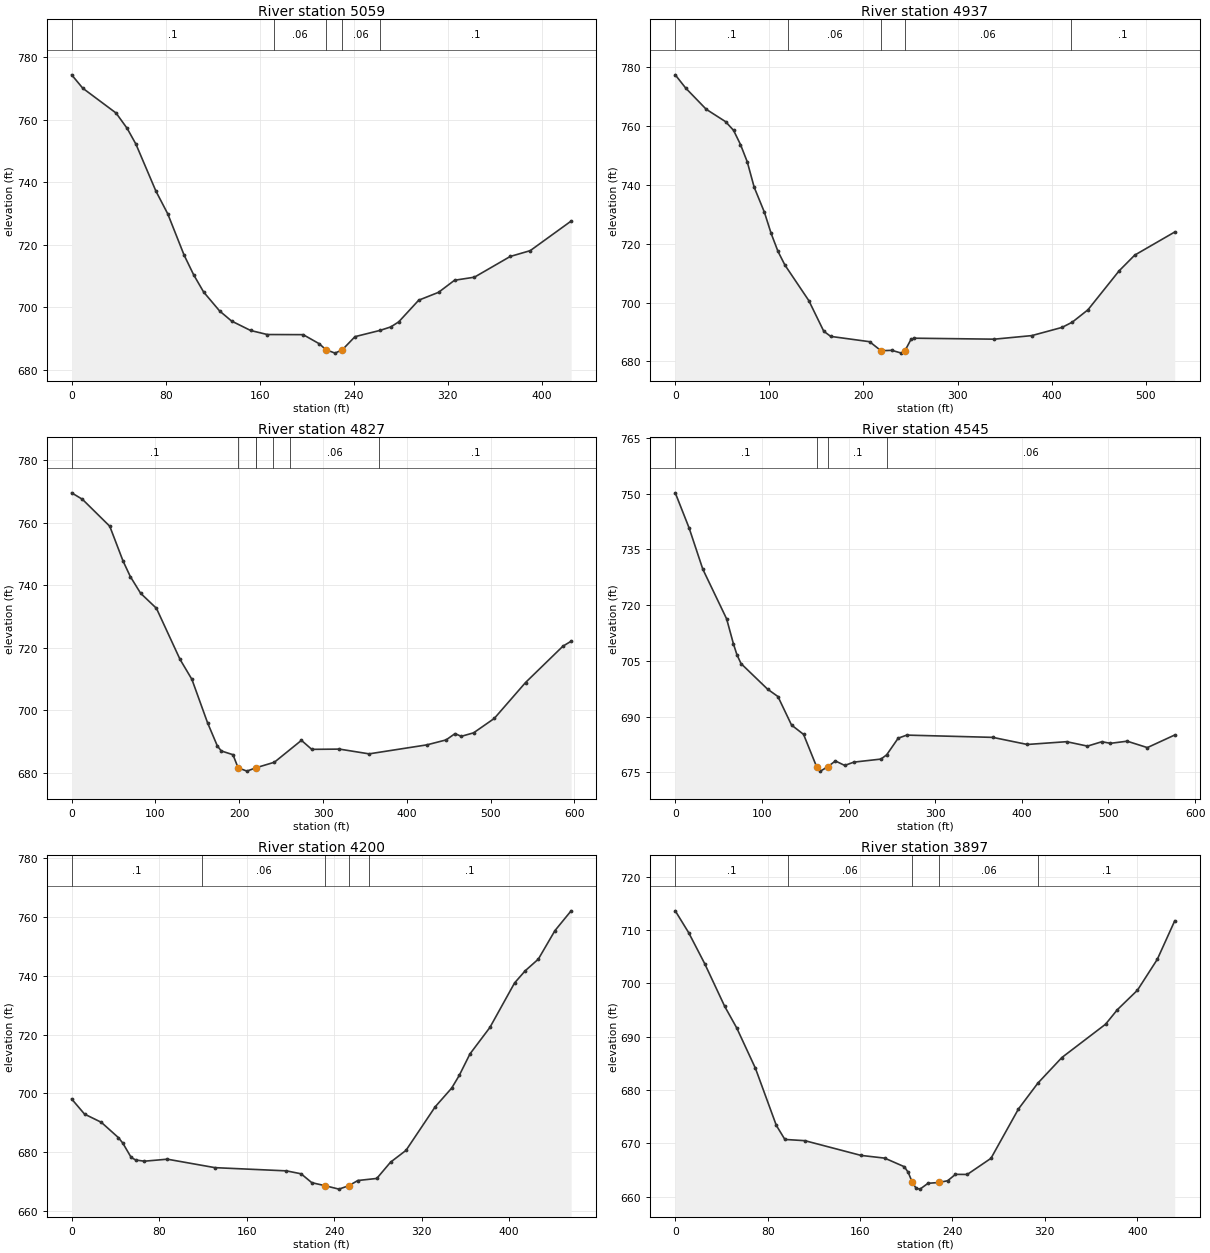
Type RM Length L Ch R = 1 ,5059    ,109.4,121.8,131.4
XS GIS Cut Line= 6
1609431.65310549507062.623841512 1609516.3770174507084.488955262
1609588.99793515507103.2303876011609685.82549741507128.218526605
1609758.44641516 507146.959630851609843.17032708507168.824088428
#Sta/Elev= 30
       0  774.35     9.5  770.06    37.8  762.13    47.2  757.24    54.7  752.18
    71.7  737.16    81.8  729.87    95.7  716.68   103.8   710.4   112.3  704.88
   125.9  698.82   136.1  695.59   152.3  692.57   166.5  691.28     197  691.24
   210.6  688.35  216.33686.4508   224.1  685.33  230.37686.4182   241.1   690.6
   262.5  692.61   271.6  693.72   278.3  695.33   295.3  702.26   312.2  704.78
   325.8  708.64   342.7  709.62   373.2  716.25   390.2  718.11     425  727.57
#Mann= 5 ,-1,0
       0      .1       0   172.5     .06       0  216.33    .045       0
  230.37     .06       0   262.5      .1       0
Bank Sta=216.33,230.37
XS Rating Curve= 0 ,0
Exp/Cntr(USF)=0,0
Exp/Cntr=0.3,0.1

Type RM Length L Ch R = 1 ,4937    ,120.3,110.1,104.3
XS GIS Cut Line= 4
1609395.82470995507103.2832602461609576.83880992507189.165862419
1609600.62168437507286.2792664151609828.54089782507319.971671883
#Sta/Elev= 30
       0  777.33    11.1  772.83    32.9  765.63    53.5  761.42      62  758.45
    69.3  753.66    76.5  747.78    83.9  739.12    94.7  730.68   101.9  723.44
   109.2  717.33   116.5  712.73   141.9  700.65   157.8  690.24   165.2  688.49
   206.5  686.69  218.64  683.62   230.1  683.76   240.3  682.81  244.07  683.62
   250.4  687.44   253.8  687.88     339  687.55   378.8  688.76     411  691.55
   421.9  693.34   438.5  697.53   471.6  710.76   488.2   716.1   530.7  723.95
#Mann= 5 ,-1,0
       0      .1       0     120     .06       0  218.64    .045       0
  244.07     .06       0  420.34      .1       0
Bank Sta=218.64,244.07
XS Rating Curve= 0 ,0
Exp/Cntr(USF)=0,0
Exp/Cntr=0.3,0.1

Type RM Length L Ch R = 1 ,4827    ,280,282.4,279.1
XS GIS Cut Line= 4
1609326.66802576507162.3248837591609597.61939013507363.055398257
1609686.73847711507417.6714417671609827.56376678507354.691825584
#Sta/Elev= 30
       0   769.5    12.9  767.42    45.5  758.81    61.3  747.73      70  742.74
    82.3   737.4   101.2  732.58   129.3  716.28   143.5  709.88   162.2  695.98
   173.9  688.57   178.6  686.99   192.5  685.79  198.61681.6196   209.1  680.54
  219.94681.6121   241.9  683.38   274.2  690.38   286.5   687.5   319.6  687.58
   354.9  686.06     424  688.94   446.8  690.52   457.5  692.53   464.9  691.66
   479.6  692.78   504.3  697.38   541.6  708.86   586.3   720.5     596  722.06
#Mann= 7 ,-1,0
       0      .1       0  198.61    .045       0  219.94      .1       0
     220     .06       0     240      .1       0     260     .06       0
  367.21      .1       0
Bank Sta=198.61,219.94
XS Rating Curve= 0 ,0
Exp/Cntr(USF)=0,0
Exp/Cntr=0.3,0.1

Type RM Length L Ch R = 1 ,4545    ,336.2,344.8,346.8
XS GIS Cut Line= 4
 1609143.2475366507365.6970914691609268.42970956507449.018941251
1609346.99915778507478.3906975931609686.13836081507524.631313395
#Sta/Elev= 30
       0   750.2      16  740.74    31.8  729.66    59.3  716.29    67.2  709.53
    71.1  706.71    75.9  704.27   106.6  697.38   118.5  695.41   134.2  687.74
   148.1  685.22   163.2   676.5   167.5  675.34  176.04676.5192   184.8  678.08
   195.6  676.87   206.1  677.76   237.4  678.58     244  679.72   257.3   684.2
   267.2  685.03   366.5  684.42   406.3  682.51   451.7  683.26   475.8  682.07
   492.4  683.25   502.3  682.82   521.6  683.39   544.9  681.67   576.5  685.06
#Mann= 4 ,-1,0
       0      .1       0   163.2    .045       0  176.04      .1       0
  244.26     .06       0
Bank Sta=163.2,176.04
XS Rating Curve= 0 ,0
Exp/Cntr(USF)=0,0
Exp/Cntr=0.3,0.1

Type RM Length L Ch R = 1 ,4200    ,296.1,302.8,308.5
XS GIS Cut Line= 6
1609068.40935592507539.1643531771609159.16245526507599.643234834
1609228.45726417507645.433497593  1609304.338346507710.564272836
1609356.38122092507765.0841769281609411.77612326507835.003328428
#Sta/Elev= 30
       0  698.12    11.8  692.97    27.1  690.19    42.8  684.96    46.8   683.1
    54.4  678.25    58.6  677.36    66.5  676.96    87.5  677.64   131.1  674.76
   196.4  673.67   209.8  672.67   219.6  669.65  231.71668.6299   244.4  667.46
  253.44668.6295   261.7  670.39     279  671.09   291.6  676.63   305.7  680.63
   332.4  695.45   347.5  701.82   354.4  706.12   364.2  713.43   382.4  722.42
     405  737.57   414.7   741.7   426.7  745.66   441.9  755.36   456.7  762.09
#Mann= 5 ,-1,0
       0      .1       0  119.06     .06       0  231.71    .045       0
  253.44     .06       0  272.12      .1       0
Bank Sta=231.71,253.44
XS Rating Curve= 0 ,0
Exp/Cntr(USF)=0,0
Exp/Cntr=0.3,0.1

Type RM Length L Ch R = 1 ,3897    ,434.8,447.5,462.1
XS GIS Cut Line= 6
1608928.42833668507577.8430815941608956.87381785507660.590291426
1608981.25533076507731.5166587531609008.75921276507829.305505171
1609029.93207067507904.2171007541609057.63116226 507990.29173176
#Sta/Elev= 30
       0  713.59    11.6   709.5    25.5  703.69    42.8  695.69    53.2  691.65
    69.4  684.09    87.5  673.38    94.9  670.75   112.2  670.52   160.8  667.76
   181.3  667.25   198.3  665.64   201.7  664.57  205.24 662.688   208.5  661.61
   211.9  661.44   218.8  662.53  228.36662.6872   235.8  663.01   242.6  664.21
   252.8  664.19   273.3  667.21   297.1  676.46   313.9   681.3   334.7   686.1
   372.5  692.34   382.8  695.08   400.1  698.71   417.3   704.5   432.4  711.72
#Mann= 5 ,-1,0
       0      .1       0    97.5     .06       0  205.24    .045       0
  228.36     .06       0  314.08      .1       0
Bank Sta=205.24,228.36
XS Rating Curve= 0 ,0
Exp/Cntr(USF)=0,0
Exp/Cntr=0.3,0.1

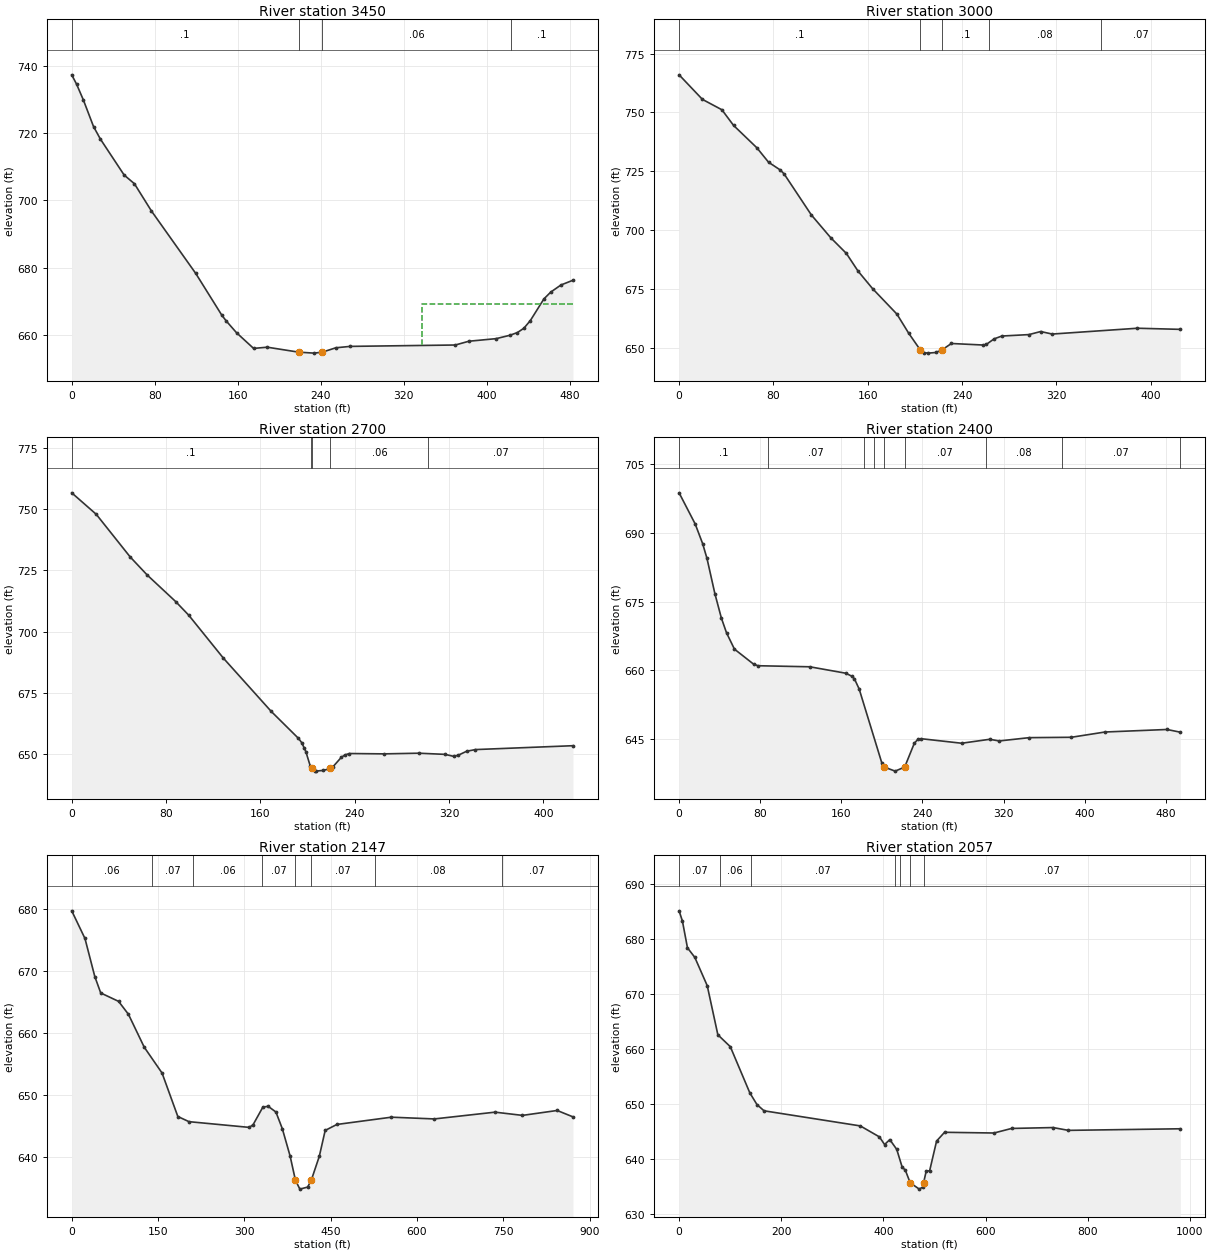
Type RM Length L Ch R = 1 ,3450    ,458.2,449.4,438.5
XS GIS Cut Line= 5
1608600.96999868507613.7340299081608603.74399789507804.405681493
1608581.38882779507807.9139746111608546.44484949507826.920740016
1608534.47560585508056.431668546
#Sta/Elev= 30
       0  737.25     4.6  734.52    11.2   729.8      21   721.9    27.6  718.19
    50.5  707.51    60.4  704.93    76.8  696.84   119.5   678.3   144.7  665.86
     149  664.15   158.8   660.7   175.2  656.06   188.4  656.42   218.6654.9506
   233.5  654.66   241.4654.9495   254.5  656.25   268.3  656.66   369.5  657.07
   382.6  658.19   408.9  658.96     422  659.95   429.4  660.77   435.6  662.05
   441.8  664.32   454.9  670.76   461.5  672.78   471.3  674.88   482.9  676.29
#Mann= 4 ,-1,0
       0      .1       0   218.6    .045       0   241.4     .06       0
   423.1      .1       0
#XS Ineff= 2 , 0
                          337.76          669.19
Permanent Ineff=
       F       F
Bank Sta=218.6,241.4
XS Rating Curve= 0 ,0
Exp/Cntr(USF)=0,0
Exp/Cntr=0.3,0.1

Type RM Length L Ch R = 1 ,3000    ,297,300.3,303.6
XS GIS Cut Line= 6
1608153.10016292507644.5906515121608143.64512934507731.578338429
1608135.54048675507806.1392129211608125.36301367507905.621953592
 1608120.8269335507980.5706225931608116.40961951508068.105880588
#Sta/Elev= 30
       0  765.96    19.8  755.53    36.3  751.13    46.2  744.49      66  734.97
    75.9  728.84    85.8  725.57    89.1  723.88   112.2  706.46   128.7  696.75
   141.9  690.13   151.8  682.62   164.1  675.19   184.8  664.34   194.7  656.29
  204.37649.3154   207.9  647.99   211.2  647.79   217.8  648.06  223.42 649.316
     231  651.88   257.9  651.23   260.6  651.48   267.2  653.84   273.8  655.05
   296.8  655.66   306.7  656.96   316.5  655.89   388.8  658.36   425.2  657.88
#Mann= 5 ,-1,0
       0      .1       0  204.37    .045       0  223.42      .1       0
   262.5     .08       0  357.59     .07       0
Bank Sta=204.37,223.42
XS Rating Curve= 0 ,0
Exp/Cntr(USF)=0,0
Exp/Cntr=0.3,0.1

Type RM Length L Ch R = 1 ,2700    ,293.9,300,303.7
XS GIS Cut Line= 6
1607952.11106358 507575.952337341607912.31882034507653.880659178
1607878.21127701507720.6764573451607832.73400576 507809.73730284
1607798.62646243507876.5327729281607755.59702092507952.808210924
#Sta/Elev= 30
       0  756.68    20.8  747.92    49.6  730.51    64.1  723.11    88.1  712.35
    99.2  706.78   128.6  689.25   169.2  667.51   192.2  656.56     195   654.8
     197  652.76   198.6  651.04   202.3  645.21  203.93644.2332     206  643.19
   206.8  643.16   213.4  643.46  219.34 644.232   221.4  644.87   228.7  648.82
   231.8  649.78   235.5  650.34   264.9   650.2   294.4  650.47   316.5     650
   323.9  649.19   327.6   649.6   334.9  651.27   342.4  651.95   425.1  653.53
#Mann= 5 ,-1,0
       0      .1       0   202.5     .06       0  203.93    .045       0
  219.34     .06       0   302.5     .07       0
Bank Sta=203.93,219.34
XS Rating Curve= 0 ,0
Exp/Cntr(USF)=0,0
Exp/Cntr=0.3,0.1

Type RM Length L Ch R = 1 ,2400    ,259,252.7,240.3
XS GIS Cut Line= 6
1607801.88629842507478.0604727571607727.76210284507524.616810083
1607665.35868435507566.2200733421607582.15347017507621.689450592
1607519.69165283507663.2051155871607479.34060875507814.812993455
#Sta/Elev= 30
       0  698.72    15.9  691.92    23.2  687.66    27.5  684.43    35.3  676.74
    41.7  671.42    46.8  668.19    54.6  664.64    73.4  661.38    77.8  661.02
   128.9  660.79   164.4  659.39   170.5  658.72   172.9  658.18   177.6  655.96
   199.9  639.87  202.43 638.921   213.1  638.04   222.5  638.92     232  644.11
   235.4  644.94   238.8  645.11   278.7  644.12   306.3  644.98   315.8  644.62
   345.4  645.34   386.9  645.42   420.1  646.57   481.2  647.12   494.4  646.53
#Mann= 9 ,-1,0
       0      .1       0   87.53     .07       0  182.53     .06       0
  192.53     .07       0  202.43    .045       0   222.5     .07       0
  302.53     .08       0  377.53     .07       0  494.42     .06       0
Bank Sta=202.43,222.5
XS Rating Curve= 0 ,0
Exp/Cntr(USF)=0,0
Exp/Cntr=0.3,0.1

Type RM Length L Ch R = 1 ,2147    ,89.7,89.8,90.4
XS GIS Cut Line= 4
1607708.68575859507136.3266671681607525.99384669507193.130034733
1607450.76776532507489.4286817621607357.11897015507851.742053258
#Sta/Elev= 30
       0  679.66      23  675.21    40.1  669.09    50.4  666.45    81.4   665.1
    98.5  663.03     126  657.73     157  653.57   184.4  646.58   203.8  645.75
   308.5  644.83   315.2  645.26   332.2  648.09   341.4  648.22   354.9   647.3
     366  644.62   379.5  640.24  388.76636.3476   396.5   634.9     410  635.23
   416.4  636.35   430.3  640.18   440.5  644.34   460.8   645.3   555.6  646.47
   630.2  646.19   735.7  647.28   783.4  646.76   843.7  647.55   871.2  646.52
#Mann= 8 ,-1,0
       0     .06       0     140     .07       0  211.32     .06       0
  331.32     .07       0  388.76    .045       0   416.4     .07       0
  527.02     .08       0  747.02     .07       0
Bank Sta=388.76,416.4
XS Rating Curve= 0 ,0
Exp/Cntr(USF)=0,0
Exp/Cntr=0.3,0.1

Type RM Length L Ch R = 1 ,2057    ,240.6,249.3,247.1
XS GIS Cut Line= 4
1607676.44600943 507068.776716551607447.69731302507148.608476371
 1607349.4428394 507521.668430921607251.18836577 507860.95341016
#Sta/Elev= 30
       0  685.13     6.5  683.28    16.4   678.4    30.8  676.66    55.1  671.51
    75.9  662.58   100.3  660.41   138.5  652.01   152.4  649.89   166.3  648.75
   354.8     646   392.2     644   402.3  642.61   412.5  643.51   426.1  641.73
   436.5  638.56     443  637.92  452.44635.6516   470.2   634.5     477  634.88
  478.57635.6375   483.8  637.77   490.5  637.84   504.1  643.25   519.7  644.84
   616.4  644.71     651  645.54   732.1   645.7   762.2  645.19   981.3  645.48
#Mann= 7 ,-1,0
       0     .07       0      80     .06       0     140     .07       0
  422.28     .06       0  432.28     .07       0  452.44    .045       0
  478.57     .07       0
Bank Sta=452.44,478.57
XS Rating Curve= 0 ,0
Exp/Cntr(USF)=0,0
Exp/Cntr=0.3,0.1