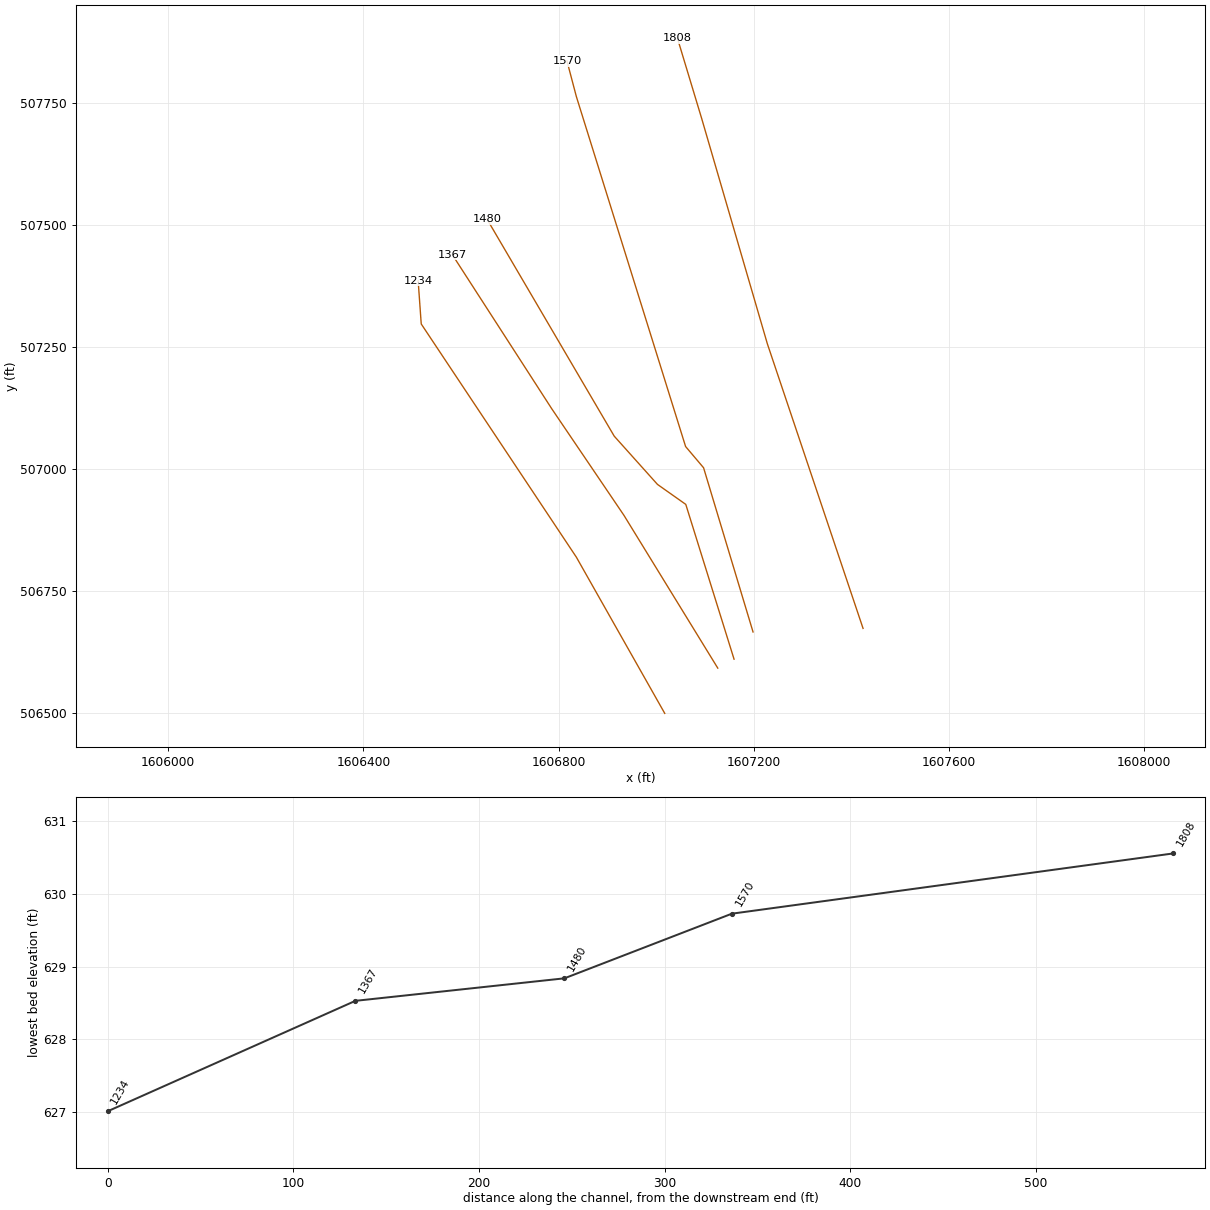
HEC-RAS study FishRn.prj: FishRn

--- FishRn.g01 (geometry) --- (continued)

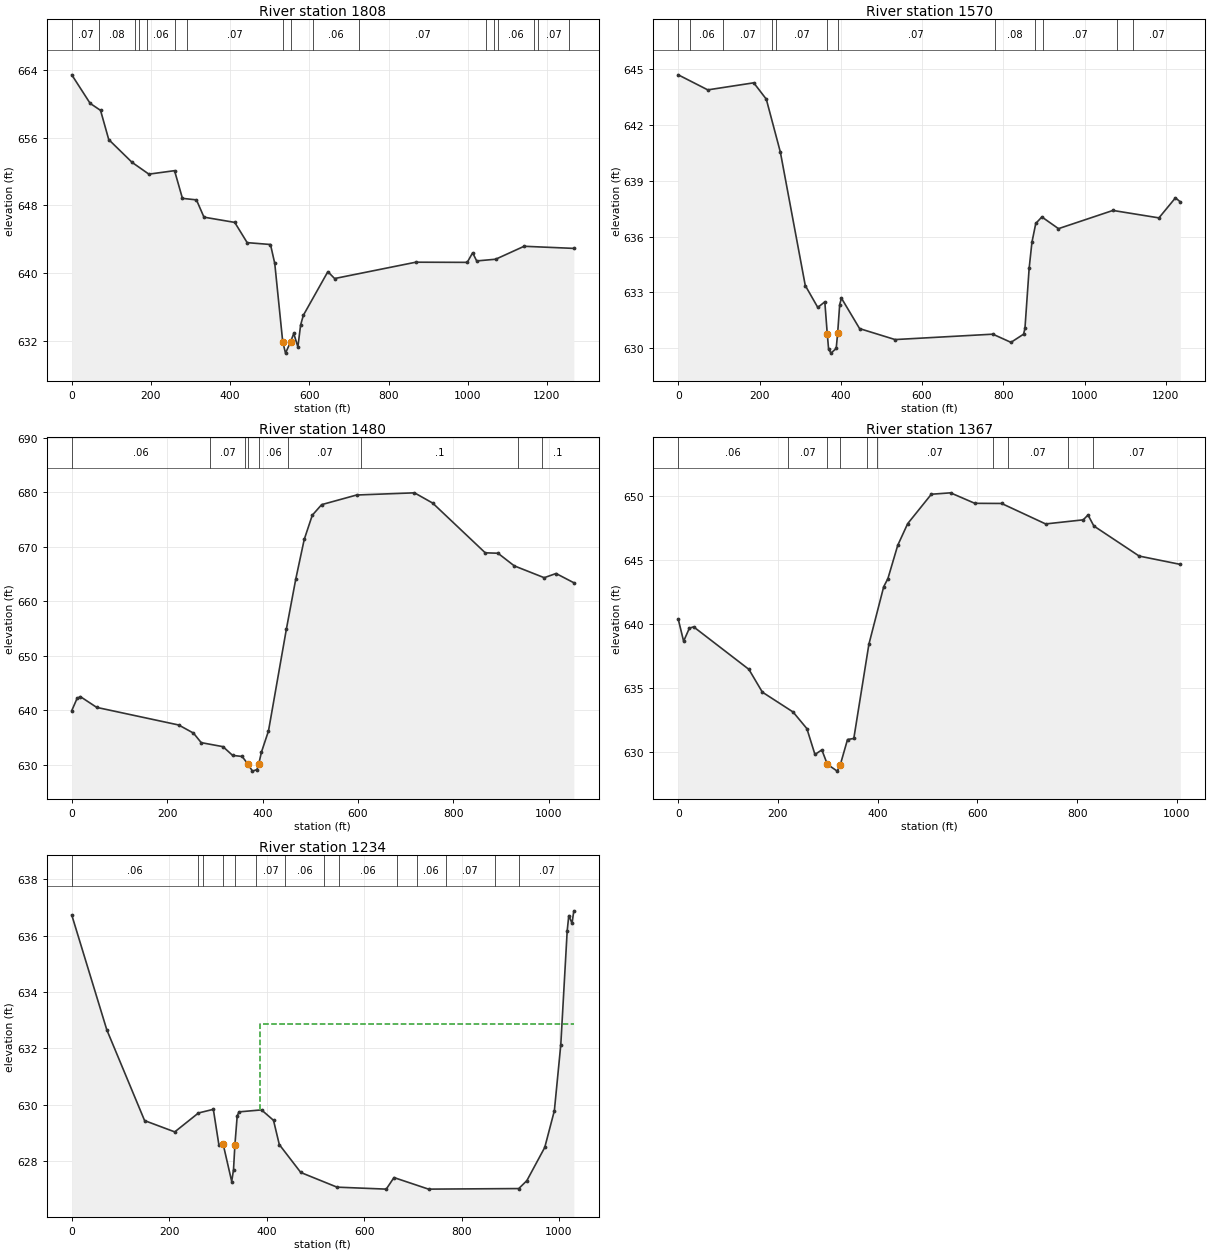
Type RM Length L Ch R = 1 ,1808    ,235.2,237.9,242.1
XS GIS Cut Line= 4
1607424.03489217506673.5038712641607227.86710628507256.889808418
1607093.10836641507719.1634603721607043.63996823507882.920916415
#Sta/Elev= 30
       0  663.43    46.4  660.06    72.7  659.23    93.4  655.78   152.3  653.09
   194.8   651.7   259.6  652.11   279.5  648.84   314.9  648.66   333.9  646.62
   411.6     646     443  643.61   501.9  643.39   512.7  641.15  532.85631.8796
   539.9  630.56  552.83 631.918   560.7  632.88   571.1  631.29     578  633.88
   584.9  635.03   646.8  640.18   663.9  639.37     869   641.3   998.8  641.28
  1012.5  642.41  1022.7  641.45  1070.6  641.65  1142.5  643.18  1268.1  642.93
#Mann= 17 ,-1,0
       0     .07       0      70     .08       0     160     .06       0
     170     .08       0     190     .06       0     260     .08       0
     290     .07       0  532.85    .045       0  552.83     .07       0
     610     .06       0  725.48     .07       0 1045.48     .06       0
 1065.48     .07       0 1075.48     .06       0    1167     .08       0
    1177     .07       0    1257     .08       0
Bank Sta=532.85,552.83
XS Rating Curve= 0 ,0
Exp/Cntr(USF)=0,0
Exp/Cntr=0.3,0.1

Type RM Length L Ch R = 1 ,1570    ,86.9,90.2,93.1
XS GIS Cut Line= 5
1607198.55618853506666.1588993491607097.18557359507002.712082847
1607060.30054465507046.2657314611606836.46457192507763.369866315
1606817.12072243507836.600153689
#Sta/Elev= 30
       0  644.71    72.7   643.9   185.8  644.28   216.7   643.4   251.3  640.55
   312.6  633.37   343.4  632.19   360.7  632.49  366.67630.7842     370  629.95
   375.8  629.73   388.7  629.98  392.27630.8015   397.3  632.34   401.6  632.69
   446.3  631.05   533.6  630.46   774.2  630.75   818.8  630.31   849.8  630.75
   853.2  631.06   863.5  634.29   870.4   635.7   879.8  636.71   894.8  637.06
   935.7  636.43  1069.7  637.41  1182.9  637.01  1223.6  638.09  1235.5  637.87
#Mann= 12 ,-1,0
       0     .07       0      30     .06       0     110     .07       0
     230     .08       0     240     .07       0  366.67    .045       0
  392.27     .07       0  778.56     .08       0  878.56     .06       0
  898.56     .07       0 1078.56      .1       0 1118.56     .07       0
Bank Sta=366.67,392.27
XS Rating Curve= 0 ,0
Exp/Cntr(USF)=0,0
Exp/Cntr=0.3,0.1

Type RM Length L Ch R = 1 ,1480    ,119,112.6,108.6
XS GIS Cut Line= 5
1607159.63483293506610.3890184141607060.69803657506927.669089498
1607002.70060422506968.6084535091606913.99864887507067.545249868
 1606653.0102033507512.760833485
#Sta/Elev= 30
       0  639.95    11.1  642.19      18  642.52    52.3  640.54   224.1  637.31
   255.1  635.82   271.3  634.07     317  633.33   337.1  631.73   357.1  631.53
   369.3  630.12   378.7  628.84   388.1  629.12  391.92630.1609   397.5  632.32
   412.3  636.22     450  655.01   469.6  664.15   487.2  671.37   504.1  675.82
   523.7  677.76     597  679.53   718.3  679.93   756.4  678.05   866.6  668.92
   893.3  668.84   927.5  666.52   990.2  664.35    1015  665.12  1052.3  663.42
#Mann= 9 ,-1,0
       0     .06       0     290     .07       0  362.35     .06       0
   369.3    .045       0  391.92     .06       0  453.34     .07       0
  606.22      .1       0  936.22     .07       0  986.22      .1       0
Bank Sta=369.3,391.92
XS Rating Curve= 0 ,0
Exp/Cntr(USF)=0,0
Exp/Cntr=0.3,0.1

Type RM Length L Ch R = 1 ,1367    ,132.7,133.4,133.4
XS GIS Cut Line= 4
1607126.26339174506592.0858637941606933.87637318506905.344307628
1606785.80887722507123.9201349981606582.34197801507439.193102587
#Sta/Elev= 30
       0   640.4    10.8  638.68    22.4   639.7    30.9   639.8   141.7  636.48
   168.7   634.7   230.3  633.15     258  631.85   274.2  629.83     288  630.19
     299629.0675   318.8  628.53  325.05629.0355   339.5     631   352.1  631.08
   382.4  638.45   412.1  642.94   420.4  643.56   440.2  646.17   460.1  647.86
   507.6  650.16   546.1  650.27   594.8  649.45   648.5  649.44   736.8  647.84
   812.2  648.16   821.8  648.54   833.5  647.68   924.4  645.33  1006.9  644.68
#Mann= 10 ,-1,0
       0     .06       0     220     .07       0     299    .045       0
  325.05     .07       0  377.62     .06       0  397.62     .07       0
  631.63      .1       0  661.63     .07       0  781.63      .1       0
  831.63     .07       0
Bank Sta=299,325.05
XS Rating Curve= 0 ,0
Exp/Cntr(USF)=0,0
Exp/Cntr=0.3,0.1

Type RM Length L Ch R = 1 ,1234    ,,,
XS GIS Cut Line= 4
1607017.56867818506499.3161155271606836.45832299506819.418138656
1606518.46223422507297.4652389871606512.14443113507385.914482221
#Sta/Elev= 30
       0  636.73    71.9  632.66   149.5  629.44   211.4  629.04     260  629.71
   290.6  629.84   301.9  628.59   310.8   628.6   328.3  627.28     332   627.7
   334.9  628.59   339.6  629.61   343.3  629.75   389.5  629.82   414.1  629.45
     426  628.59   470.1   627.6   544.5  627.08   645.5  627.01   661.4  627.42
   732.3  627.01   917.5  627.03   934.1  627.31   970.9  628.49   990.6  629.79
  1003.8  632.13  1016.9  636.16  1020.2  636.71  1026.8  636.44  1030.6  636.88
#Mann= 14 ,-1,0
       0     .06       0     260      .1       0     270     .06       0
   310.8    .045       0   334.9     .06       0  377.79     .07       0
  437.79     .06       0  517.79     .07       0  547.79     .06       0
  667.79     .07       0  707.79     .06       0  767.79     .07       0
  867.79     .06       0  917.79     .07       0
#XS Ineff= 2 , 0
                          387.34          632.87
Permanent Ineff=
       F       F
Bank Sta=310.8,334.9
XS Rating Curve= 0 ,0
Exp/Cntr(USF)=0,0
Exp/Cntr=0.3,0.1
LCMann Table=0

Chan Stop Cuts=-1
Use User Specified Reach Order=0
Composite Channel Slope=5